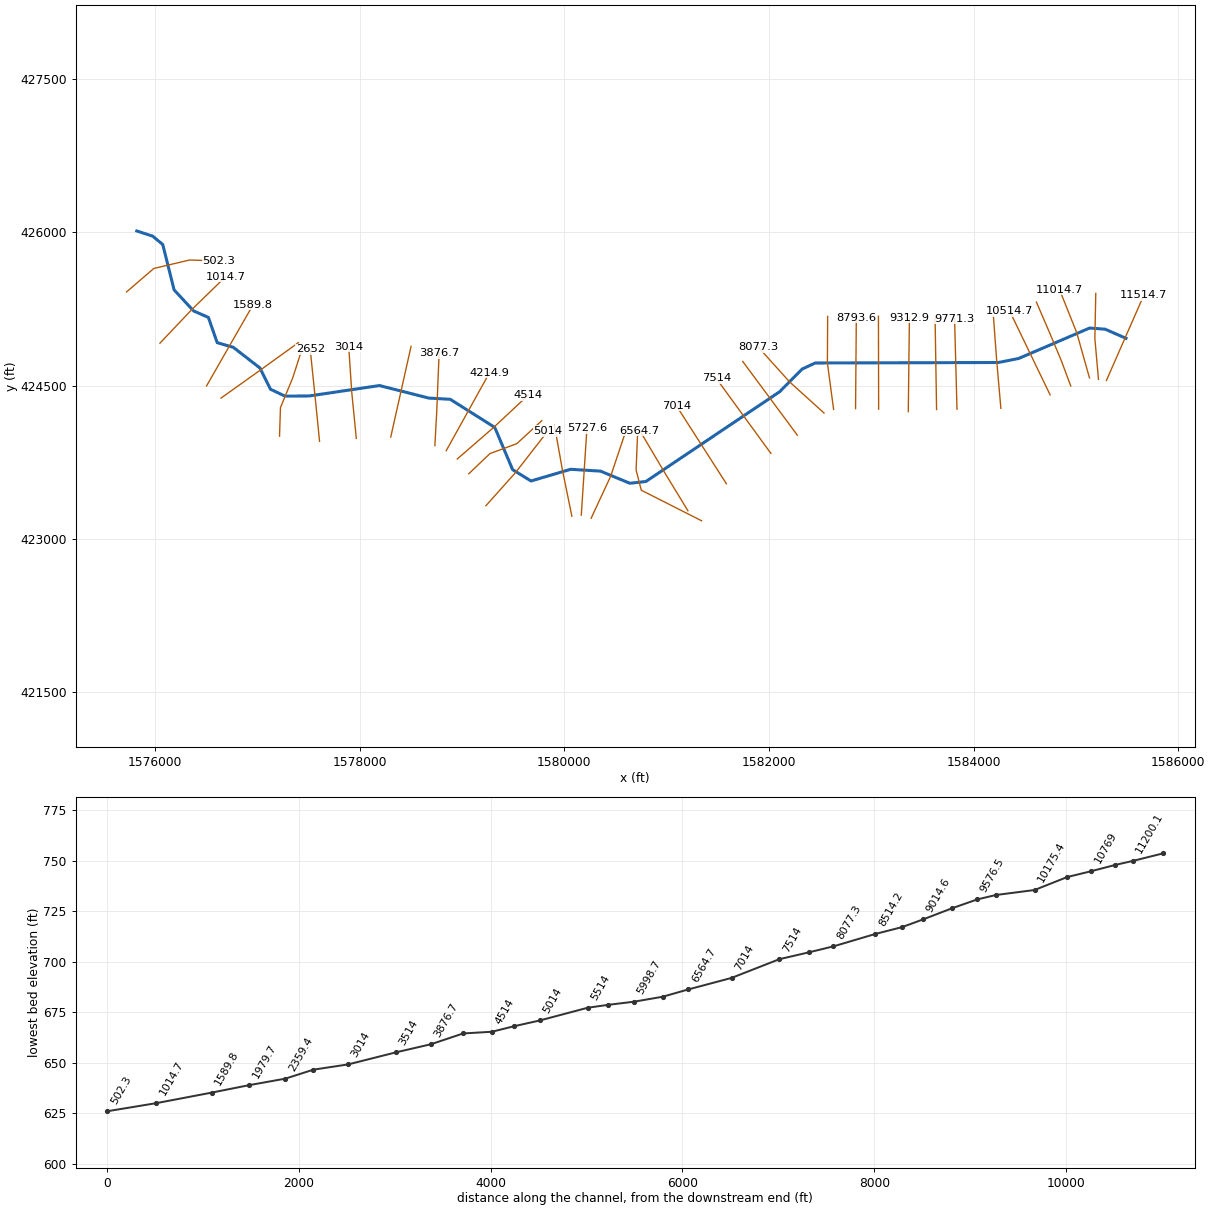
--- RFCENCMPCR.prj (project) ---

Proj Title=RFCENCMPCR
Current Plan=p01
Default Exp/Contr=0,0
English Units
Geom File=g01
Flow File=f01
Plan File=p01
BEGIN DESCRIPTION:
END DESCRIPTION:
DSS Export Rating Curves= 0
DSS Export Rating Curve Sorted= 0
DSS Export Volume Flow Curves= 0
DXF OffsetX= 0
DXF OffsetY= 0
DXF ScaleX= 0
DXF ScaleY= 0

--- RFCENCMPCR.p01 (plan) ---

Plan Title=Floodplain
Program Version=4.00
Geom File=g01
Flow File=f01
K Sum by GR=0
Std Step Tol=0.01
Critical Tol=0.01
Num of Std Step Trials=20
Max Error Tol=0.3
Flow Tol Ratio=0.001
Split Flow NTrial=30
Split Flow Tol=0.02
Split Flow Ratio=0.02
Log Output Level=0
Friction Slope Method=1
Unsteady Friction Slope Method=2
Unsteady Bridges Friction Slope Method=1
Global Log Level=0
CheckData=False
Run HTab=0
Run UNet=0
Run PostProcess=0
UNET Theta=0
UNET Theta Warmup=0
UNET ZTol=0
UNET ZSATol=0
UNET MxIter=0
UNET MaxInSteps=0
UNET DtIC=0
UNET DtMin=0
UNET MaxCRTS=0
UNET WFStab=0
UNET SFStab=0
UNET WFX=0
UNET SFX=0
UNET DSS MLevel=0
UNET DZMax Abort=0
UNET Convert EG Bridges=0
UNET Use Existing IB Tables=0
UNET Froude Limit=0
UNET Froude Power=0
Write IC File=0
Echo Input=False
Echo Output=False
Write Detailed=0

--- RFCENCMPCR.f01 (steady flow) ---

Flow Title=NFF Regression Equation
Program Version=4.00
Number of Profiles=1
Profile Names=P100yr
River Rch & RM=RFCENCMPCR,Main      ,11514.7
     366
River Rch & RM=RFCENCMPCR,Main      ,10175.4
     405
River Rch & RM=RFCENCMPCR,Main      ,9576.5
     432
River Rch & RM=RFCENCMPCR,Main      ,8077.3
     477
River Rch & RM=RFCENCMPCR,Main      ,6564.7
     522
River Rch & RM=RFCENCMPCR,Main      ,6296.1
     622
River Rch & RM=RFCENCMPCR,Main      ,3876.7
     689
River Rch & RM=RFCENCMPCR,Main      ,2359.4
     742
Boundary for River Rch & Prof#=RFCENCMPCR,Main      ,1
Up Type=0
Dn Type=3
Dn Slope=0.008786

--- RFCENCMPCR.g01 (geometry) ---

Geom Title=USGS 10m DEM
Program Version=4.00

River Reach=RFCENCMPCR      ,Main
Reach XY= 30
     1585490.563       424962.51     1585286.204      425052.295
      1585135.05      425063.261     1584440.764      424765.014
     1584241.691      424725.576     1582452.085      424720.919
     1582323.817      424661.361     1582105.181      424439.986
     1580797.257      423560.133     1580639.751      423542.584
     1580352.918      423661.475     1580060.759      423679.408
     1579673.631      423564.967     1579493.609       423675.96
     1579319.314      424089.866     1578883.897      424365.219
     1578675.005      424377.127      1578192.05      424499.827
     1577505.886      424397.952     1577267.984      424396.467
     1577126.429      424463.687     1577023.959      424671.361
     1576763.168      424874.464     1576605.486      424920.007
     1576519.557      425167.062     1576374.159      425231.535
     1576183.895      425437.513     1576073.204       425881.58
     1575974.872      425963.433     1575819.446       426014.32

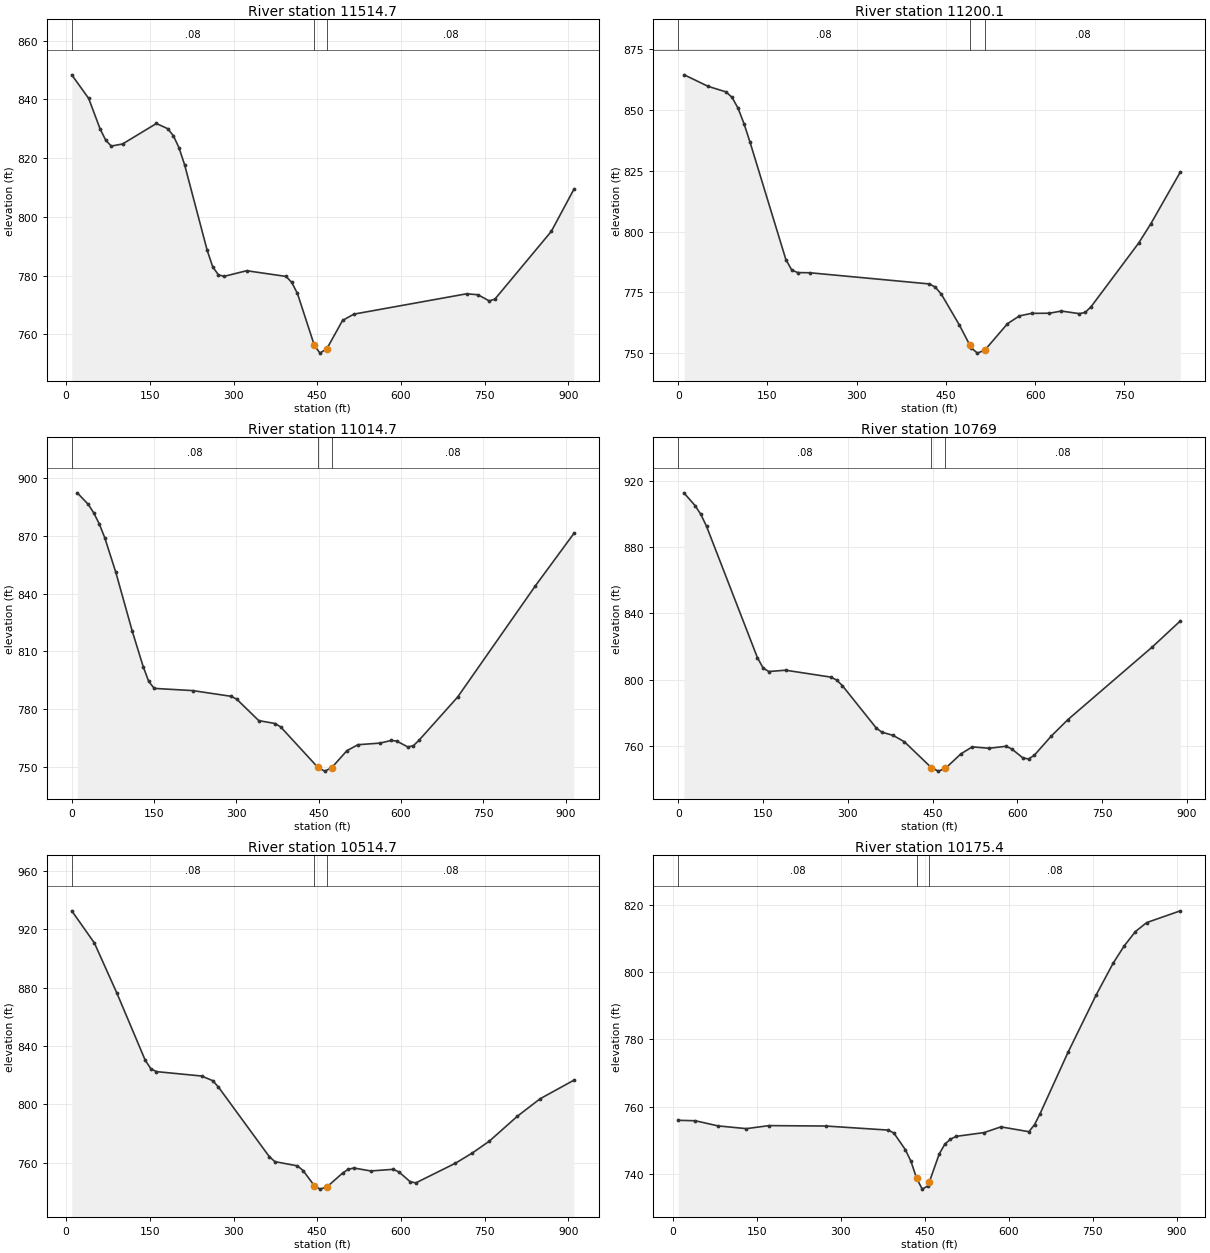
Type RM Length L Ch R = 1 ,11514.7 ,303.2,314.6,326
XS GIS Cut Line= 3
     1585298.973      424549.687     1585481.401      424966.519
     1585663.826      425383.343
#Sta/Elev= 30
    10.1  848.35    40.4  840.32    60.7  830.05    70.8  826.15    80.9  824.11
   101.1  824.82   161.8  831.79     182  830.03   192.1  827.67   202.2  823.57
   212.3  817.78   252.8  788.64   262.9  782.95     273   780.3   283.1  779.78
   323.6   781.7   394.3  779.75   404.4  777.71   414.6  773.95   444.9  756.29
     455  753.66   467.5  755.22   495.4  764.77   515.7  766.93   717.9  773.85
   738.1  773.52   758.3  771.44   768.4  772.01   869.6  795.09     910  809.38
#Mann= 3 , 0 , 0
    10.1     .08       0   444.9    .045       0   467.5     .08       0
Bank Sta=444.9,467.5
XS Rating Curve= 0 ,0
Exp/Cntr=0.3,0.1

Type RM Length L Ch R = 1 ,11200.1 ,177.8,185.4,195.9
XS GIS Cut Line= 3
     1585221.327      424560.074      1585185.98      424960.673
     1585194.817      425402.511
#Sta/Elev= 30
    10.1  864.54    50.3  859.79    80.4  857.51    90.5  855.24   100.5  850.84
   110.6  844.42   120.6  836.89     181  788.45     191   784.1   201.1   783.1
   221.2  783.03   422.4  778.42   432.5  777.06   442.6   774.1   472.8  761.48
   490.6  753.09     493  752.01   503.1  749.93   515.6  751.19   553.6  762.05
   573.8  765.28     594   766.3   624.2  766.37   644.2  767.26   674.2   766.2
   684.2  766.68   694.2  769.06   774.2  795.27   794.2  803.03   844.2  824.51
#Mann= 3 , 0 , 0
       0     .08       0   490.6    .045       0   515.6     .08       0
Bank Sta=490.6,515.6
XS Rating Curve= 0 ,0
Exp/Cntr=0.3,0.1

Type RM Length L Ch R = 1 ,11014.7 ,242.3,245.7,246.2
XS GIS Cut Line= 3
     1585133.404      424574.725     1585008.394      425018.398
     1584840.396      425440.118
#Sta/Elev= 30
      10  892.28    30.1  886.29    40.1  881.84    50.1  876.18    60.1     869
    80.2  851.11   110.2  820.55   130.3     802   140.3  794.42   150.3  790.84
   220.5  789.69   290.6  786.72   300.6  785.25   340.7  774.13   370.8   772.6
   380.8  770.81   448.4  749.89   460.9  747.92   473.4  749.63   501.3  758.51
   521.5  761.62   561.8  762.46     582  763.83   592.1  763.53   612.3  760.47
   622.4  761.08   632.4  763.82   703.1  786.33   844.3  843.84   914.9  871.19
#Mann= 3 , 0 , 0
       0     .08       0   448.4    .045       0   473.4     .08       0
Bank Sta=448.4,473.4
XS Rating Curve= 0 ,0
Exp/Cntr=0.3,0.1

Type RM Length L Ch R = 1 ,10769   ,252.9,254.3,255.7
XS GIS Cut Line= 4
     1584950.334      424495.271     1584856.075      424748.591
     1584732.361       425043.15     1584614.537      425317.089
#Sta/Elev= 30
      10  912.58      30   904.8      40  899.59    50.1  892.36   140.1  813.22
   150.2  806.97   160.2  804.91   190.2  805.69   270.3  801.51   280.3  799.73
   290.3   796.4   350.2  770.88   360.1  768.36   380.1  766.42   400.1  762.54
   447.5  747.04     460  744.88   472.5  746.53   499.9  755.27   519.9   759.5
   549.8  758.66   579.8  759.86   589.8  758.27   609.7  752.81   619.6  752.24
   629.5  754.34   659.4  765.87   689.2  775.93   838.3  819.65     888  835.38
#Mann= 3 , 0 , 0
       0     .08       0   447.5    .045       0   472.5     .08       0
Bank Sta=447.5,472.5
XS Rating Curve= 0 ,0
Exp/Cntr=0.3,0.1

Type RM Length L Ch R = 1 ,10514.7 ,349.4,339.4,329.4
XS GIS Cut Line= 3
     1584748.644      424408.284     1584551.185      424818.204
     1584353.725      425228.124
#Sta/Elev= 30
    10.1  932.64    50.6  910.63      91  876.23   141.6  830.39   151.7  824.45
   161.8  822.45   242.7  819.44   262.9  816.22     273  811.87     364  764.26
   374.1  760.77   414.6  757.86   424.7  754.66   444.9  744.28     455  741.92
   467.5  743.43   495.4  752.89   505.6   755.5   515.7  756.39     546  754.37
   586.4   755.5   596.6  753.67   616.8  746.95   626.9  746.22   697.7  759.67
     728  766.67   758.3  774.73   808.9  791.92   849.3  803.79     910  816.56
#Mann= 3 , 0 , 0
    10.1     .08       0   444.9    .045       0   467.5     .08       0
Bank Sta=444.9,467.5
XS Rating Curve= 0 ,0
Exp/Cntr=0.3,0.1

Type RM Length L Ch R = 1 ,10175.4 ,405.7,404.1,402.5
XS GIS Cut Line= 3
     1584266.959      424277.298     1584225.721      424751.537
     1584194.017      425180.612
#Sta/Elev= 30
    10.1  755.98    40.5  755.85      81  754.32   131.7   753.5   172.2   754.4
   273.5  754.28   384.9  753.07     395   752.2   415.3   747.3   425.4  743.84
   435.5  738.79   445.6  735.52   455.8  736.47   458.1  737.54     476  745.99
     486   748.9     496  750.36     506   751.2   556.1  752.33   586.1  754.03
   636.1  752.59   646.1  754.71   656.1     758   706.2  776.31   756.2  793.28
   786.2  802.62   806.2  807.84   826.2  812.09   846.2  814.75   906.3  818.25
#Mann= 3 , 0 , 0
    10.1     .08       0   435.5    .045       0   458.1     .08       0
Bank Sta=435.5,458.1
XS Rating Curve= 0 ,0
Exp/Cntr=0.3,0.1

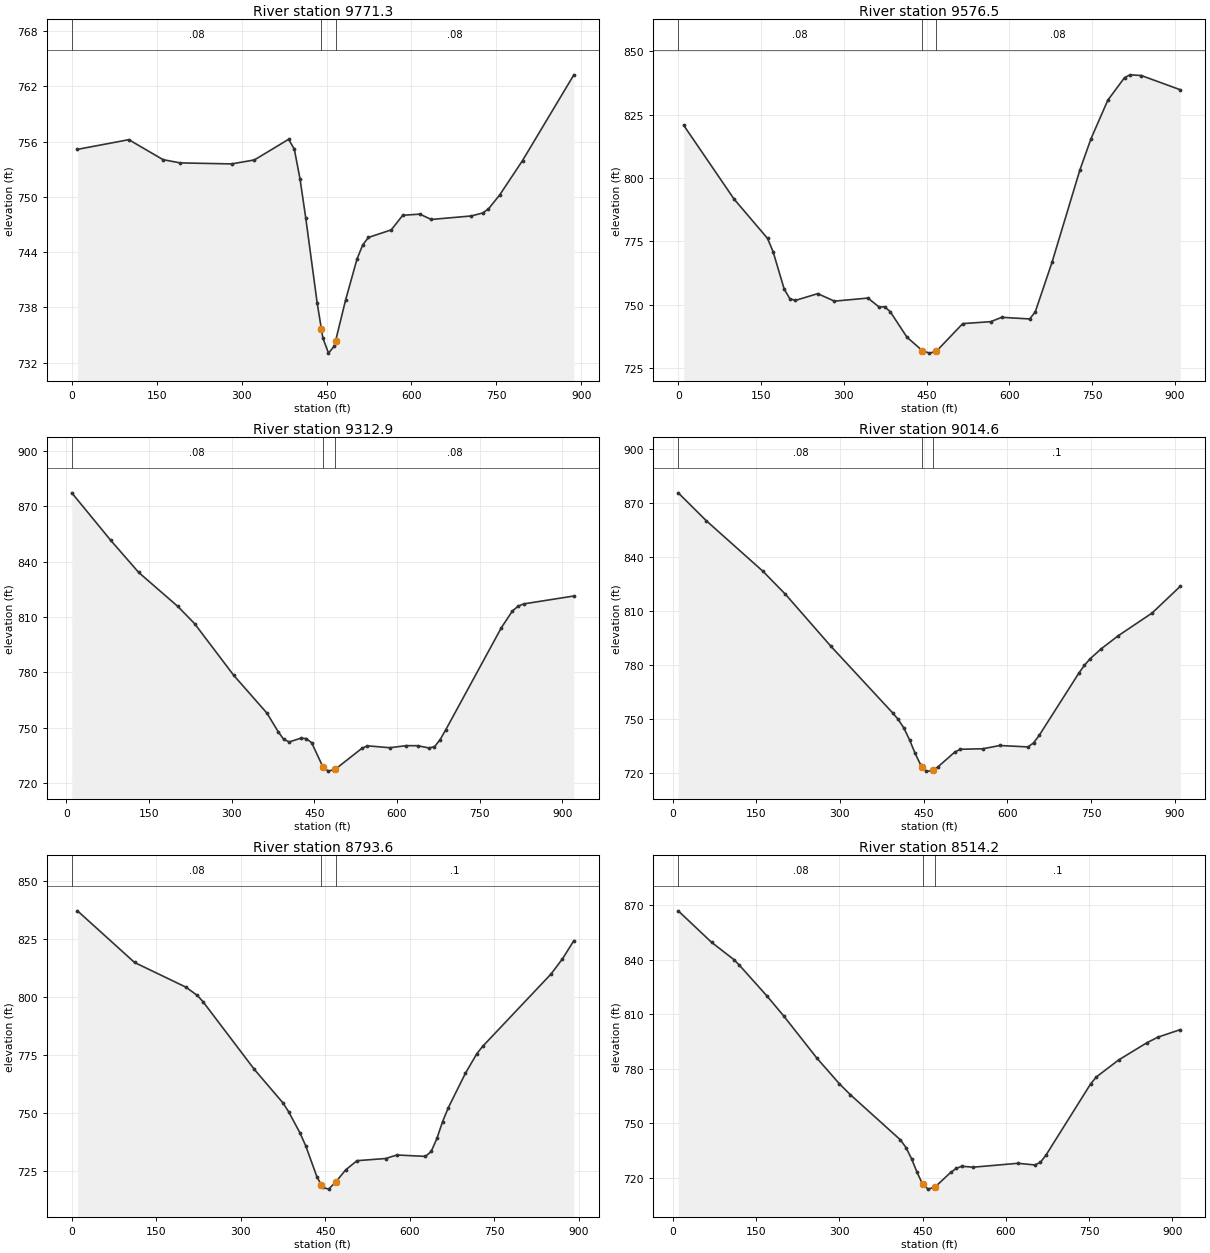
Type RM Length L Ch R = 1 ,9771.3  ,195.1,194.8,194.5
XS GIS Cut Line= 2
     1583837.935      424268.461      1583814.37      425155.082
#Sta/Elev= 30
    10.1  755.16   100.8  756.21   161.3  754.04   191.5  753.69   282.2  753.58
   322.5  754.01     383  756.25   393.1  755.19   403.2  751.95   413.2  747.76
   433.4  738.53     441  735.64   443.5  734.69   453.5  733.04   463.6   733.8
     466  734.36   483.8  738.83   503.9  743.26     514   744.8   524.1   745.6
   564.4  746.42   584.6     748   614.8  748.13     635  747.55   705.5  747.93
   725.7  748.25   735.8  748.68   755.9  750.21   796.2  753.94   886.9  763.25
#Mann= 3 , 0 , 0
       0     .08       0     441    .045       0     466     .08       0
Bank Sta=441,466
XS Rating Curve= 0 ,0
Exp/Cntr=0.3,0.1

Type RM Length L Ch R = 1 ,9576.5  ,264.4,263.6,262.9
XS GIS Cut Line= 3
     1583638.516      424265.285     1583631.106      424720.225
     1583623.695      425175.165
#Sta/Elev= 30
    10.1  820.69   101.1  791.66   161.8  776.13   171.9   770.9   192.1  756.08
   202.2  752.34   212.3  751.65   252.8  754.31   283.1  751.36   343.8  752.57
     364  749.05   374.1  749.13   384.2  747.21   414.6  737.12   442.5  731.81
     455  730.84   467.5   731.5   515.7  742.49   566.2  743.25   586.4  744.97
     637  744.33   647.1  747.13   677.4  766.64     728  803.13   748.2   815.5
   778.6  830.66   808.9  839.57     819  840.67   839.2   840.4     910  834.78
#Mann= 3 , 0 , 0
       0     .08       0   442.5    .045       0   467.5     .08       0
Bank Sta=442.5,467.5
XS Rating Curve= 0 ,0
Exp/Cntr=0.3,0.1

Type RM Length L Ch R = 1 ,9312.9  ,297.8,298.3,298.7
XS GIS Cut Line= 2
     1583361.928       424244.16     1583372.974      425164.655
#Sta/Elev= 30
    10.1  877.29    80.9  851.49   131.5  834.13   202.3  815.76   232.7  806.44
   303.5  778.49   364.2  757.83   384.4  747.84   394.5  743.66   404.6  742.28
   424.9  744.25     435  744.13   445.1  741.86   465.3  728.87   475.5  726.45
     488  727.48   536.2   738.8   546.3  740.17   586.7  739.14   617.1  740.26
   637.3  740.23   657.5  739.03   667.7  739.62   677.8  743.38   687.9  748.63
   789.1  804.17   809.3   813.3   819.4  815.81   829.5  817.08   920.6  821.37
#Mann= 3 , 0 , 0
    10.1     .08       0   465.3    .045       0     488     .08       0
Bank Sta=465.3,488
XS Rating Curve= 0 ,0
Exp/Cntr=0.3,0.1

Type RM Length L Ch R = 1 ,9014.6  ,221.3,221,220.8
XS GIS Cut Line= 3
     1583072.008      424269.048      1583071.09      424724.047
     1583070.172      425179.046
#Sta/Elev= 30
    10.1  875.83    60.7  860.22   161.8  832.22   202.2  819.41   283.1  790.68
   394.3  753.43   404.4  749.75   414.6  744.93   424.7  738.41   434.8  730.81
   444.9  724.28  447.85  723.37     455  720.99   465.1  721.13   467.5  721.64
   475.2  723.24   505.6  731.55   515.7  733.16   556.1  733.43   586.4  735.25
     637  734.46   647.1  736.75   657.2  740.95     728  775.45   738.1  779.87
   748.2  783.47   768.4  789.09   798.8  796.34   859.4  808.95     910  823.85
#Mann= 3 , 0 , 0
    10.1     .08       0  447.85    .045       0   467.5      .1       0
Bank Sta=447.85,467.5
XS Rating Curve= 0 ,0
Exp/Cntr=0.3,0.1

Type RM Length L Ch R = 1 ,8793.6  ,276,279.3,279.4
XS GIS Cut Line= 2
     1582846.451      424273.616     1582853.815      425164.655
#Sta/Elev= 30
    10.1  837.24   111.4  814.96   202.5  804.31   222.8  800.74   232.9  798.04
     324  768.82   374.7  754.39   384.8  750.58     405  741.41   415.2  735.85
   435.4  722.27   443.2   718.9   445.5  717.91   455.7  717.14   468.2  720.11
     486  725.41   506.3  729.42   556.9  730.35   577.2  731.87   627.8  731.27
   637.9  733.39   648.1  739.03   658.2  746.31   668.3  752.28   698.7  767.16
   718.9  775.56   729.1  778.71   850.6  809.97   870.8  816.48   891.1  824.37
#Mann= 3 , 0 , 0
       0     .08       0   443.2    .045       0   468.2      .1       0
Bank Sta=443.2,468.2
XS Rating Curve= 0 ,0
Exp/Cntr=0.3,0.1

Type RM Length L Ch R = 1 ,8514.2  ,417.1,436.9,457.3
XS GIS Cut Line= 3
     1582631.641      424266.552     1582571.098       424722.81
     1582573.595      425176.876
#Sta/Elev= 30
      10  866.94      70  849.61   110.1  840.14   120.1  837.02   170.1  819.97
   200.1  809.02   260.1  785.73   300.2  771.75   320.2  765.68   410.2  740.85
   420.2  736.63   430.2  730.51   440.2  722.96   450.3  716.36   460.3  713.74
   472.8  714.97   500.6  722.91   510.7  725.14   520.8  726.34     541  725.81
   621.7  727.96     652  727.06   662.1  728.42   672.2  732.39   752.9  771.73
     763  775.48   803.3  784.86   853.8  794.27     874   797.4   914.3  801.55
#Mann= 3 , 0 , 0
      10     .08       0   450.3    .045       0   472.8      .1       0
Bank Sta=450.3,472.8
XS Rating Curve= 0 ,0
Exp/Cntr=0.3,0.1

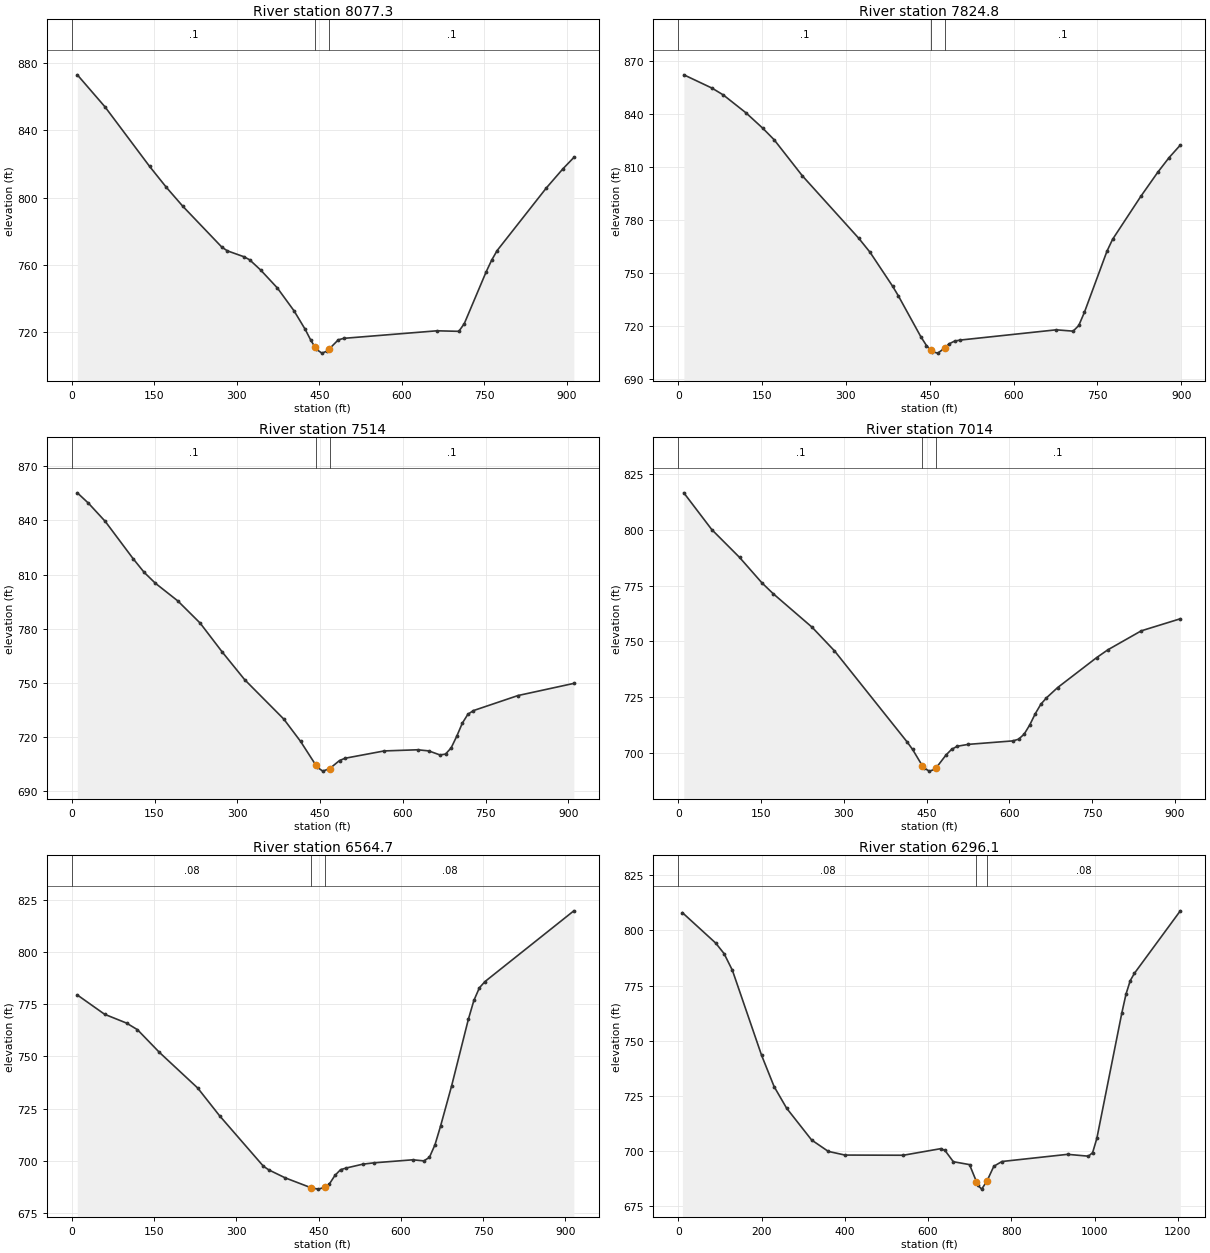
Type RM Length L Ch R = 1 ,8077.3  ,258,252.5,249.8
XS GIS Cut Line= 3
     1582537.987      424231.009     1582201.145      424536.124
     1581894.992      424876.647
#Sta/Elev= 30
    10.1  872.98    60.6  853.86   141.4  818.58   171.7   806.2     202   794.8
   272.7   770.6   282.8  768.38   313.1  764.85   323.2  763.07   343.4  756.94
   373.7  746.29     404   732.7   424.2  721.72   434.3  715.32     442  711.18
   444.4   709.9   454.5   707.6   464.4  708.85     467  709.78   484.3  715.49
   494.3  716.39   663.5  720.87   703.4  720.55   713.3  725.13   753.1  755.94
   763.1  762.88     773  768.56   862.6  805.83   892.5  817.11   912.4  823.88
#Mann= 3 , 0 , 0
       0      .1       0     442    .045       0     467      .1       0
Bank Sta=442,467
XS Rating Curve= 0 ,0
Exp/Cntr=0.3,0.1

Type RM Length L Ch R = 1 ,7824.8  ,310.9,310.7,310.5
XS GIS Cut Line= 2
     1582277.586      424013.116     1581743.699      424735.704
#Sta/Elev= 30
    10.1  862.31    60.6  854.76    80.8  850.88   121.1  840.81   151.4  832.03
   171.6  825.54   222.1  805.11     323  769.74   343.2  761.81   383.6  742.58
   393.7  737.22   434.1  713.97   444.2  708.97   451.9  706.33   454.3  705.51
   464.4  704.68   476.9  707.54   484.5  709.91   494.6  711.51   504.7  712.08
   676.3  717.88   706.6  717.13   716.7  720.33   726.8  727.81   767.2  762.45
   777.3  769.19   827.8  793.51     858   807.1   878.2  815.39   898.4  822.51
#Mann= 3 , 0 , 0
       0      .1       0   451.9    .045       0   476.9      .1       0
Bank Sta=451.9,476.9
XS Rating Curve= 0 ,0
Exp/Cntr=0.3,0.1

Type RM Length L Ch R = 1 ,7514    ,501.6,500,498.4
XS GIS Cut Line= 3
     1582018.631      423835.382     1581751.047      424203.382
     1581483.462      424571.381
#Sta/Elev= 30
    10.1  855.31    30.3  849.55    60.7  839.49   111.2  818.86   131.4  811.22
   151.7  805.22   192.1  795.51   232.6  783.23     273  767.09   313.4  751.87
   384.2   730.1   414.6  717.76   442.5  704.52   444.9  703.41     455  701.26
   467.5  702.67   485.3  707.13   495.4  708.39   566.2  712.44   626.9  713.08
   647.1  712.46   667.3  710.22   677.4  710.69   687.6  714.13   697.7  720.52
   707.8  727.76   717.9  732.73     728  734.77   808.9  743.11     910  749.83
#Mann= 3 , 0 , 0
       0      .1       0   442.5    .045       0   467.5      .1       0
Bank Sta=442.5,467.5
XS Rating Curve= 0 ,0
Exp/Cntr=0.3,0.1

Type RM Length L Ch R = 1 ,7014    ,450.3,449.3,448.3
XS GIS Cut Line= 3
     1581583.699      423537.813     1581338.522      423921.106
     1581093.346      424304.398
#Sta/Elev= 30
    10.1  816.52    60.7  800.09   111.2   787.6   151.7  776.22   171.9  771.42
   242.7  756.34   283.1  745.82   414.6   705.1   424.7  701.69   442.5  694.33
   444.9  693.44     455  691.96   465.1  692.74   467.5  693.42   485.3  699.17
   495.4  701.69   505.6  703.09   525.8  703.94   606.7   705.5   616.8  706.25
   626.9  708.49     637  712.58   647.1  717.65   657.2   721.9   667.3  724.73
   687.6  729.35   758.3  742.76   778.6  746.25   839.2  754.75     910  760.15
#Mann= 3 , 0 , 0
       0      .1       0   442.5    .045       0   467.5      .1       0
Bank Sta=442.5,467.5
XS Rating Curve= 0 ,0
Exp/Cntr=0.3,0.1

Type RM Length L Ch R = 1 ,6564.7  ,276.4,268.6,260.8
XS GIS Cut Line= 3
     1581207.204      423273.449     1580984.291      423640.316
     1580737.015      424058.857
#Sta/Elev= 30
      10  779.58    59.9  770.28    99.8  766.06   119.8  762.87   159.7     752
   229.6  734.86   269.5  721.53   349.4  697.28   359.4   695.5   389.3  691.68
     437  686.87   449.5  686.28     462   687.2   469.8  688.82   479.9  692.88
     490  695.61   500.2  696.41   530.6  698.27   550.8  698.91   621.7  700.37
     642  699.85   652.1  701.56   662.2  707.58   672.3  716.48   692.6  735.93
     723  767.79   733.1   776.9   743.2  783.01   753.4     786   915.4  819.98
#Mann= 3 , 0 , 0
       0     .08       0     437    .045       0     462     .08       0
Bank Sta=437,462
XS Rating Curve= 0 ,0
Exp/Cntr=0.3,0.1

Type RM Length L Ch R = 1 ,6296.1  ,316.5,297.4,281.5
XS GIS Cut Line= 4
     1581340.654      423175.466     1580751.537      423474.627
      1580700.91      423672.533     1580714.718      424013.116
#Sta/Elev= 30
      10  808.04    90.1  794.23   110.1  789.47   130.1  781.88   200.2  743.34
   230.3  729.14   260.3  719.36   320.4  704.92   360.4  699.76   400.4  698.09
   540.6  698.01   630.7     701   640.7  700.18   660.7  695.08   699.6  693.76
   716.3  686.04   719.1  684.51   728.8  682.64   741.3  686.22     758  693.01
   777.5  695.17   935.2  698.42   985.3  697.58   995.3  699.21  1005.4  705.64
  1065.5   762.6  1075.5  771.12  1085.6  777.19  1095.6  780.51  1205.9  808.87
#Mann= 3 , 0 , 0
       0     .08       0   716.3    .045       0   741.3     .08       0
Bank Sta=716.3,741.3
XS Rating Curve= 0 ,0
Exp/Cntr=0.3,0.1

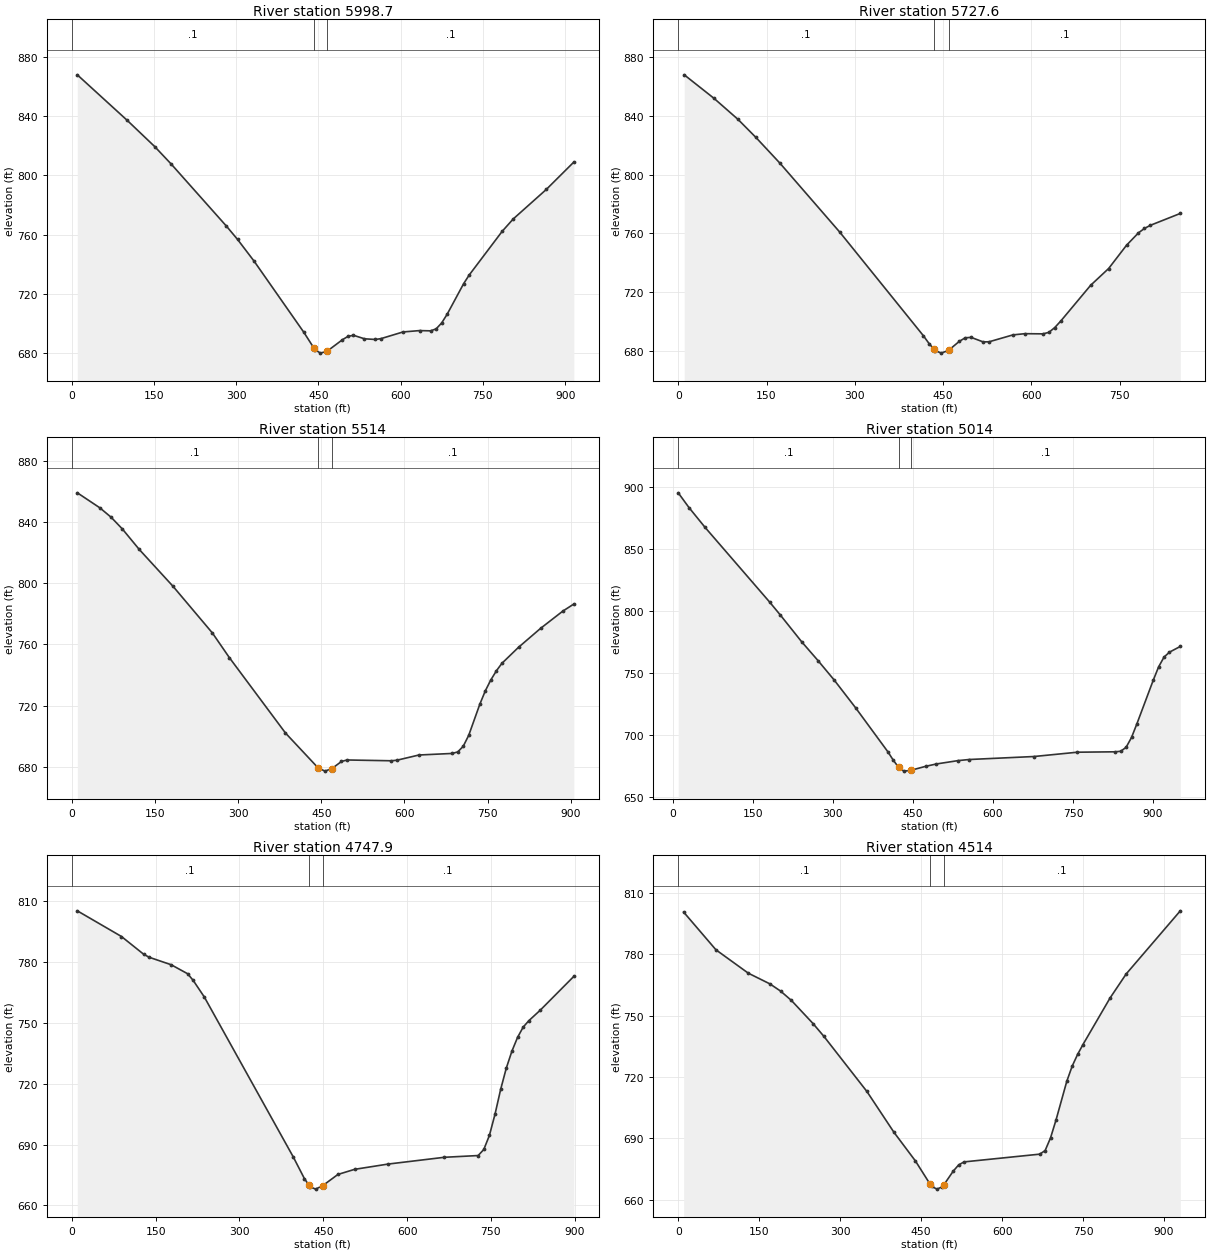
Type RM Length L Ch R = 1 ,5998.7  ,260.9,271,278.1
XS GIS Cut Line= 3
     1580261.684      423200.336     1580452.314      423611.881
     1580599.061      424050.186
#Sta/Elev= 30
    10.1  867.66   100.8   837.1   151.2  819.36   181.4  807.54   282.2   765.7
   302.4  756.78   332.6  742.13   423.3  694.22   441.1  683.92   443.5  682.57
   453.6  680.19   466.1  681.58   493.7  689.22   503.8  691.47   513.8  692.21
   533.9  689.85     554  689.38   564.1  689.97   604.3  694.46   634.4  695.37
   654.5   695.2   664.6  696.53   674.6  700.46   684.7  706.37   714.8  726.99
   724.9   732.8   785.1  762.24   805.2  770.56   865.5  790.43   915.8   808.9
#Mann= 3 , 0 , 0
       0      .1       0   441.1    .045       0   466.1      .1       0
Bank Sta=441.1,466.1
XS Rating Curve= 0 ,0
Exp/Cntr=0.3,0.1

Type RM Length L Ch R = 1 ,5727.6  ,206.3,213.6,220.3
XS GIS Cut Line= 2
     1580165.051      423230.696      1580220.28      424082.153
#Sta/Elev= 30
    10.2   867.9    60.9  851.87   101.6  837.59   132.1  825.28   172.7  807.86
   274.3     761   416.5   690.5   426.6  684.93   434.4  681.44   436.8  680.37
   446.9  678.62   459.4  680.52   477.4  686.55   487.6  689.05   497.7  689.33
     518  686.28   528.2  686.33   568.8  691.02   589.1  691.85   619.6  691.73
   629.8  692.72   639.9  696.02   650.1  700.46   700.9  724.79   731.4  736.17
   761.8  751.99   782.1  760.43   792.3  763.43   802.5  765.58   853.2  773.63
#Mann= 3 , 0 , 0
       0      .1       0   434.4    .045       0   459.4      .1       0
Bank Sta=434.4,459.4
XS Rating Curve= 0 ,0
Exp/Cntr=0.3,0.1

Type RM Length L Ch R = 1 ,5514    ,525.7,500,476.9
XS GIS Cut Line= 3
     1580072.843      423220.334     1579981.565      423667.687
      1579902.71      424109.768
#Sta/Elev= 30
    10.1  859.13    50.7  849.31      71  843.16    91.3  835.48   121.8  822.08
   182.6  798.03   253.7  767.48   284.1  751.47   385.5  702.09   444.1   679.4
   456.6  677.19   469.1  678.83   486.5   683.5   496.5  684.48   576.3  683.96
   586.3  684.31   626.2  687.73   686.1  688.75   696.1  689.74     706  693.38
     716   700.6     736  720.93     746  729.75   755.9  736.83   765.9  742.78
   775.9  747.68   805.8  758.14   845.8  770.58   885.7   781.8   905.6  786.43
#Mann= 3 , 0 , 0
       0      .1       0   444.1    .045       0   469.1      .1       0
Bank Sta=444.1,469.1
XS Rating Curve= 0 ,0
Exp/Cntr=0.3,0.1

Type RM Length L Ch R = 1 ,5014    ,279.6,266.1,250.8
XS GIS Cut Line= 3
     1579232.298      423322.174     1579520.519      423645.487
     1579838.275      424054.538
#Sta/Elev= 30
    10.1  895.39    30.2  883.52    60.4  867.51   181.3  807.32   201.5  796.79
   241.7   775.1     272  760.09   302.2  744.47   342.5  721.99   402.9  686.54
     413  679.81   423.1  673.91   433.1  670.88   445.6  671.49   473.8  674.75
   494.1  676.67   534.7  679.37     555  680.24   676.9  682.67   758.1  686.14
   829.2  686.47   839.4   686.9   849.5   690.1   859.7  698.06   869.9  709.25
   900.3  744.13   910.5  755.04   920.6  762.89   930.8  766.86   951.1  771.48
#Mann= 3 , 0 , 0
    10.1      .1       0   423.1    .045       0   445.6      .1       0
Bank Sta=423.1,445.6
XS Rating Curve= 0 ,0
Exp/Cntr=0.3,0.1

Type RM Length L Ch R = 1 ,4747.9  ,223.9,233.9,244.9
XS GIS Cut Line= 4
      1579065.06      423635.713     1579272.171       423833.62
     1579534.512      423930.272     1579778.443      424155.793
#Sta/Elev= 30
     9.9  805.28    88.9  792.62   128.4  783.92   138.3   782.4   177.8   778.7
   207.4  774.24   217.3  770.95   237.1  762.81   396.3  683.92   416.3   673.2
   423.7  670.28   426.3  669.25   436.2  668.05   448.7  669.71   476.2  675.29
   506.1  677.81     566  680.41   666.7  683.75   727.1  684.61   737.2   687.6
   747.2  694.52   757.3  705.05   767.4  717.29   777.4  727.68   787.5   736.1
   797.6  742.87   807.6  747.92   817.7  751.09   837.9  756.21   898.3  772.96
#Mann= 3 , 0 , 0
       0      .1       0   423.7    .045       0   448.7      .1       0
Bank Sta=423.7,448.7
XS Rating Curve= 0 ,0
Exp/Cntr=0.3,0.1

Type RM Length L Ch R = 1 ,4514    ,289.5,299.1,307.7
XS GIS Cut Line= 3
     1578952.461      423780.438     1579314.079      424095.109
     1579643.092      424403.018
#Sta/Elev= 30
      10  800.52    69.9  782.09   129.8  770.69   169.8  765.47   189.7  761.93
   209.7  757.37   249.7   746.1   269.6  739.92   349.5  712.94   399.5  693.05
   439.4  679.01   466.9  667.55   469.4  666.57   479.4  665.28   489.4  666.48
   491.9  667.35   509.4  674.07   519.4   677.1   529.4  678.57   669.6  682.35
   679.6  684.11   689.6  690.29   699.7  698.96   719.7   717.9   729.7  725.32
   739.7  731.01   749.7  735.87   799.8  758.55   829.8  770.34     930  801.13
#Mann= 3 , 0 , 0
       0      .1       0   466.9    .045       0   491.9      .1       0
Bank Sta=466.9,491.9
XS Rating Curve= 0 ,0
Exp/Cntr=0.3,0.1

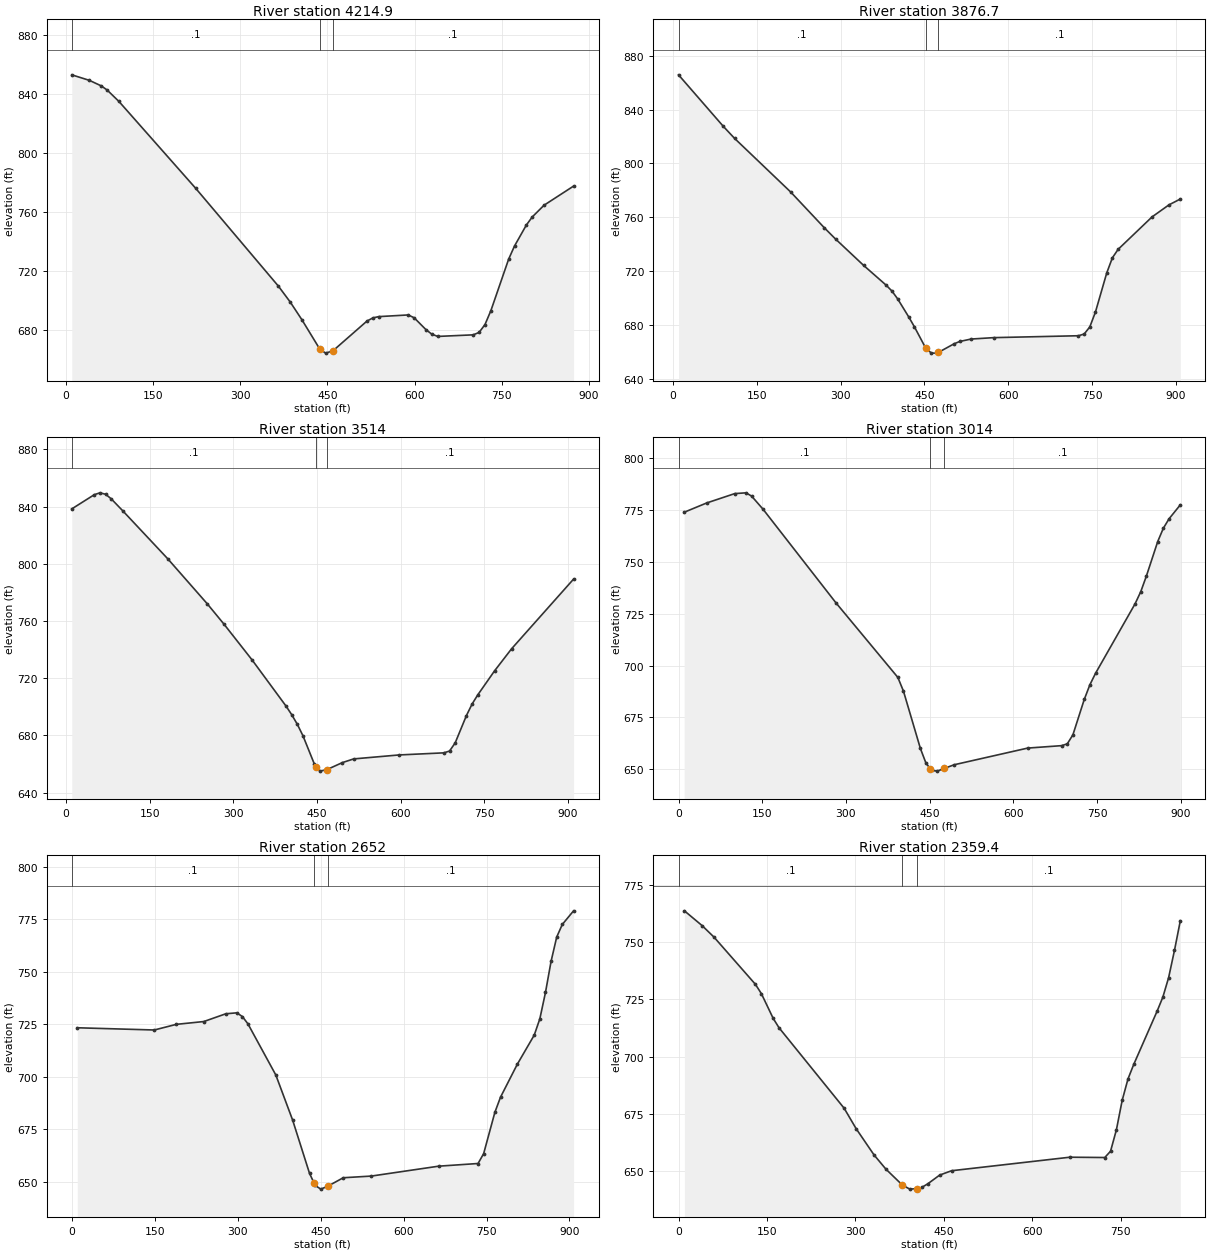
Type RM Length L Ch R = 1 ,4214.9  ,325.4,338.2,351.1
XS GIS Cut Line= 2
     1578844.141      423861.235     1579267.569      424625.245
#Sta/Elev= 30
    10.2  852.91    40.6  849.15    60.9  845.43    71.1  842.61    91.4  834.87
   223.5  776.02   365.7  709.81     386  699.08   406.3  686.96   436.8  667.25
   446.9  664.45   459.4  665.97     518  686.14   528.2   688.3   538.3  689.17
   589.1  690.31   599.3  688.38   619.6  680.34   629.7  677.27   639.9  675.76
   700.8  676.83     711  678.48   721.1  683.79   731.3  693.27   761.8  728.08
   771.9  736.98   792.2  751.14   802.4  756.65   822.7   764.6   873.5  777.56
#Mann= 3 , 0 , 0
    10.2      .1       0   436.8    .045       0   459.4      .1       0
Bank Sta=436.8,459.4
XS Rating Curve= 0 ,0
Exp/Cntr=0.3,0.1

Type RM Length L Ch R = 1 ,3876.7  ,367.6,362.7,357.7
XS GIS Cut Line= 3
     1578733.682      423911.862     1578752.092      424252.445
     1578775.104      424818.549
#Sta/Elev= 30
      10  865.89    90.3  827.52   110.3  818.66   210.7   778.8   270.9   752.2
   290.9  743.88   341.1  724.29   381.5  709.56   391.7  705.26   401.8  699.54
     422  685.88   432.1  678.55   452.4  662.66   462.5  659.08   472.6  659.13
     475  659.64     503  666.02   513.1  667.74   533.3  669.54   573.8  670.59
   725.5     672   735.7  673.29   745.8  678.58   755.9  689.67   776.1  718.72
   786.2  729.94   796.4  736.19   857.1   760.3   887.4  769.27   907.7  773.59
#Mann= 3 , 0 , 0
      10      .1       0   452.4    .045       0     475      .1       0
Bank Sta=452.4,475
XS Rating Curve= 0 ,0
Exp/Cntr=0.3,0.1

Type RM Length L Ch R = 1 ,3514    ,491.2,500,507.9
XS GIS Cut Line= 3
     1578302.257      423995.747     1578401.512      424439.789
     1578500.767      424883.831
#Sta/Elev= 30
    10.1  838.41    50.6  848.38    60.7  849.66    70.8  848.66    80.9  845.46
   101.1  837.28     182  803.66   252.8  772.21   283.1  757.85   333.7  732.72
   394.3   700.6   404.4  694.64   414.6  687.83   424.7  679.83   444.9  660.28
  448.94  658.23     455  655.09   467.5  656.12   495.4  661.06   515.7  663.63
   596.6  666.39   677.4  667.87   687.6  669.14   697.7  674.84   717.9  693.96
     728  701.98   738.1  708.34   768.4  725.24   798.8   740.6     910  789.35
#Mann= 3 , 0 , 0
    10.1      .1       0  448.94    .045       0   467.5      .1       0
Bank Sta=448.94,467.5
XS Rating Curve= 0 ,0
Exp/Cntr=0.3,0.1

Type RM Length L Ch R = 1 ,3014    ,361.9,362,363
XS GIS Cut Line= 3
     1577965.494      423982.149     1577921.031      424433.589
     1577891.429      424878.381
#Sta/Elev= 30
    10.1  773.98    50.4  778.46   100.8  782.99     121  783.36     131  781.78
   151.2  775.55   282.3  730.25   393.1  694.32   403.2  687.67   433.5  660.05
   443.5  652.96   451.3  650.29   453.6   649.5   463.8   649.1   476.3  650.39
   494.1  652.18   625.9  660.22   686.6  661.39   696.8  662.26   706.9  666.63
   727.2  683.67   737.3  690.76   747.4  696.28   818.3  729.82   828.5  735.68
   838.6  743.23   858.9  759.86     869  766.29   879.1   770.8   899.4  777.56
#Mann= 3 , 0 , 0
       0      .1       0   451.3    .045       0   476.3      .1       0
Bank Sta=451.3,476.3
XS Rating Curve= 0 ,0
Exp/Cntr=0.3,0.1

Type RM Length L Ch R = 1 ,2652    ,306.5,292.6,277.9
XS GIS Cut Line= 3
     1577606.076      423953.284     1577573.858       424280.06
     1577514.712      424856.031
#Sta/Elev= 30
      10  723.38   149.3  722.32   189.1  725.01   238.8  726.35   278.6  730.05
   298.5   730.5   308.5  728.72   318.4  725.32     369  700.88   399.5  679.32
   429.9  654.05   437.8  649.58   440.1  648.28   450.3   646.5   462.8  647.86
   490.9  651.92   541.7  652.72   663.6  657.44   734.7  658.71   744.8  663.41
   765.1  683.09   775.3  690.31   805.8  706.07   836.3  719.89   846.4  727.64
   856.6   740.2   866.7     755   876.9  766.59     887   772.6   907.4   779.1
#Mann= 3 , 0 , 0
       0      .1       0   437.8    .045       0   462.8      .1       0
Bank Sta=437.8,462.8
XS Rating Curve= 0 ,0
Exp/Cntr=0.3,0.1

Type RM Length L Ch R = 1 ,2359.4  ,394.7,379.7,365.5
XS GIS Cut Line= 4
     1577214.866      424003.911     1577224.071      424284.662
     1577343.735      424574.618     1577421.977      424818.549
#Sta/Elev= 30
      10  763.67    40.1  757.19    60.2  752.17   130.4  731.55   140.5  727.48
   160.5  716.67   170.5  712.54   280.9  677.37   301.1  668.49   331.5     657
   351.7  650.77   379.7  643.79   392.2  642.05   404.7  642.27   412.4  642.79
   422.6  644.37   442.8  648.19     463  650.09   663.5     656   722.7  655.86
   732.5  658.62   742.4  667.95   752.2  680.82   762.1  690.23   771.9   696.6
   811.3  719.74   821.2  725.96     831  734.52   840.9  746.41   850.8  759.35
#Mann= 3 , 0 , 0
       0      .1       0   379.7    .045       0   404.7      .1       0
Bank Sta=379.7,404.7
XS Rating Curve= 0 ,0
Exp/Cntr=0.3,0.1

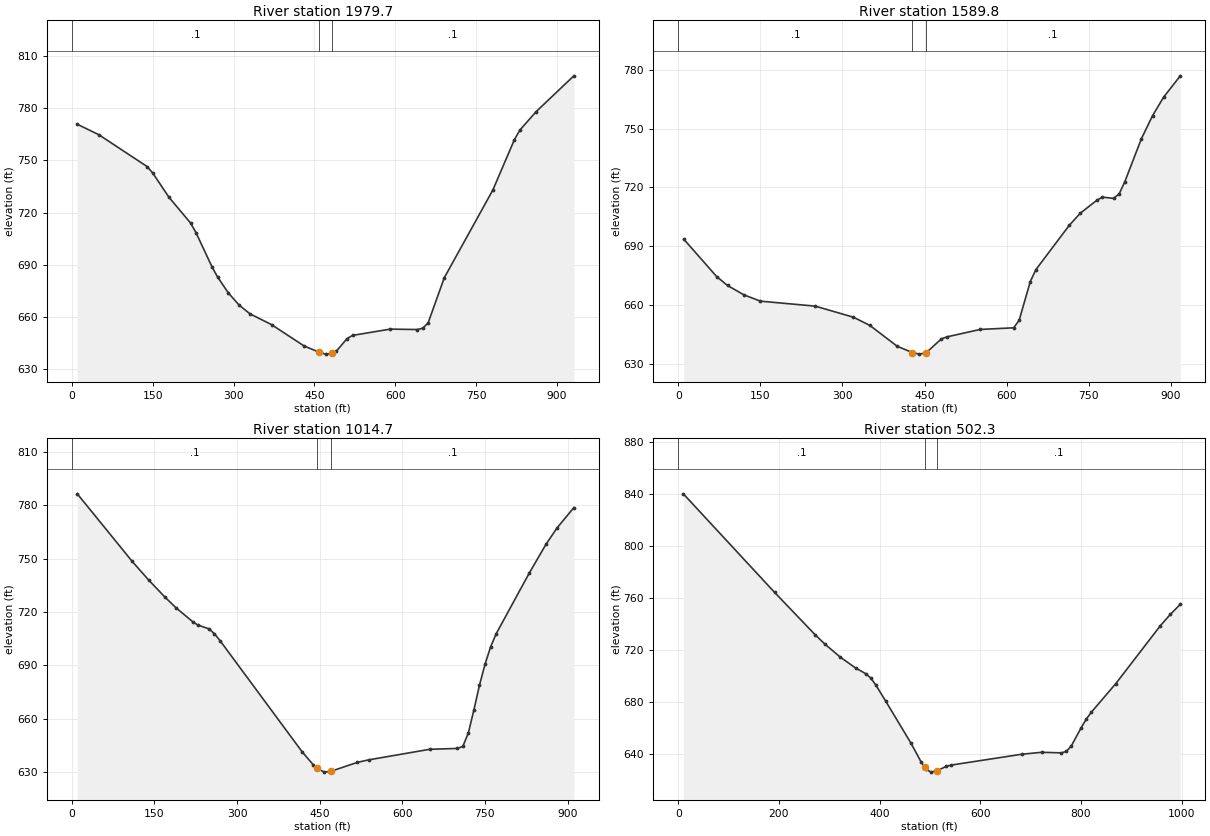
Type RM Length L Ch R = 1 ,1979.7  ,378.7,389.9,401
XS GIS Cut Line= 3
      1576643.17      424377.306     1577034.444      424656.616
     1577399.569      424920.557
#Sta/Elev= 30
      10  770.83    50.1   764.8   140.2  746.42   150.2  742.78   180.3  728.87
   220.3  714.12   230.4  708.58   260.4  688.73   270.4  683.13   290.4  673.96
   310.5  666.94   330.5  661.95   370.6  655.75   430.7  643.54   458.2  639.98
   470.7  638.81   483.2  639.25   490.7   640.5   510.8  647.78   520.8  649.57
   590.9  653.17   640.9  652.93   650.9  653.66     661  656.73     691  682.68
   781.1  733.07   821.1     762   831.2  767.46   861.2  777.99   931.3   798.6
#Mann= 3 , 0 , 0
       0      .1       0   458.2    .045       0   483.2      .1       0
Bank Sta=458.2,483.2
XS Rating Curve= 0 ,0
Exp/Cntr=0.3,0.1

Type RM Length L Ch R = 1 ,1589.8  ,580.8,575.1,568.4
XS GIS Cut Line= 3
     1576501.482      424496.376     1576724.843      424887.421
     1576957.127      425292.604
#Sta/Elev= 30
      10  693.71    70.1  674.65    90.1  670.08   120.1   665.3   150.1   662.1
   250.2  659.57   320.2  653.92   350.3  649.72   400.3  639.09   427.8  635.94
   440.3  635.12   452.8  635.75   480.8  642.89     491  643.91   551.9   647.7
   612.8  648.52   622.9  652.33   643.2  672.01   653.4  678.12   714.3  700.65
   734.6  706.88   765.1  713.53   775.2  715.08   795.5  714.44   805.7  716.76
   815.9  722.86   846.3  744.81   866.6  756.53   886.9     766   917.4  776.86
#Mann= 3 , 0 , 0
       0      .1       0   427.8    .045       0   452.8      .1       0
Bank Sta=427.8,452.8
XS Rating Curve= 0 ,0
Exp/Cntr=0.3,0.1

Type RM Length L Ch R = 1 ,1014.7  ,528.5,512.4,497.5
XS GIS Cut Line= 3
     1576045.838      424915.201     1576360.808      425248.034
     1576685.581       425564.15
#Sta/Elev= 30
      10  786.54   109.6  748.54   139.5  738.06   169.3  728.38   189.3  722.39
   219.2  714.66   229.1  712.65     249  710.57     259   707.8     269  703.99
   418.4  641.28   438.3  634.11   445.7  632.03   458.2  629.92   470.7  630.42
   518.7  635.42   538.8  636.81   649.6  642.76     700  643.26     710  644.41
   720.1  652.08   730.2  665.14   740.2  678.88   750.3  690.69   760.4  700.44
   770.5   707.8   830.9  742.13   861.1  758.22   881.2  767.44   911.5  778.79
#Mann= 3 , 0 , 0
       0      .1       0   445.7    .045       0   470.7      .1       0
Bank Sta=445.7,470.7
XS Rating Curve= 0 ,0
Exp/Cntr=0.3,0.1

Type RM Length L Ch R = 1 ,502.3   ,474.8,502.3,529.7
XS GIS Cut Line= 4
     1575719.062       425416.87     1575986.005      425646.994
     1576335.793      425729.839     1576621.147      425720.634
#Sta/Elev= 30
    10.1  839.97   191.3  764.22   271.9  731.59     292  724.15   322.2  714.27
   352.4  705.98   372.4  701.64   382.4  698.31   392.4  692.98   412.4  680.34
   462.3  648.21   482.2  633.94   489.7  629.55   492.2  628.08   502.2   625.9
   514.7  627.03   532.2   630.3   542.2  631.32     682  639.64   721.8  641.15
   761.1  640.73     771  641.83   780.8  646.02   800.5  660.08   810.4  666.55
   820.2  671.78   869.4  694.07     958  738.65   977.7  747.28   997.4  754.99
#Mann= 3 , 0 , 0
       0      .1       0   489.7    .045       0   514.7      .1       0
Bank Sta=489.7,514.7
XS Rating Curve= 0 ,0
Exp/Cntr=0.3,0.1

Chan Stop Cuts=-1
Use User Specified Reach Order=0